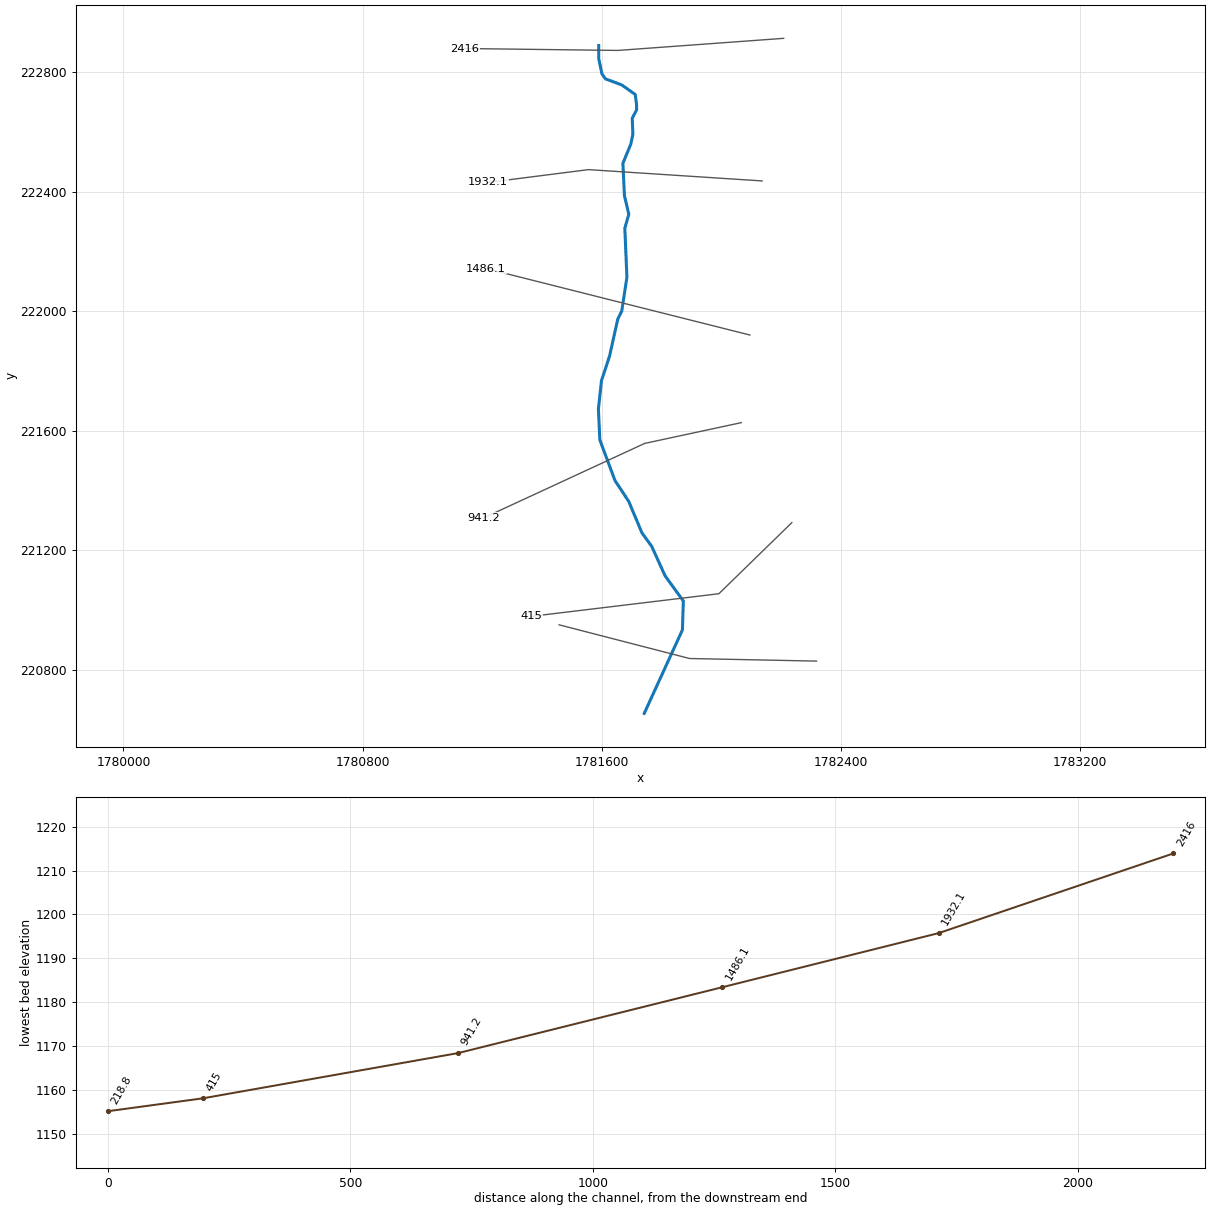
--- DblcampBr2.prj (project) ---

Proj Title=DblcampBr2
Current Plan=p01
Geom File=g01
Flow File=f01
Plan File=p01
DSS Export Rating Curves=0
DSS Export Rating Curve Sorted=0
DSS Export Volume Flow Curves=0
DXF OffsetX=0
DXF OffsetY=0
DXF ScaleX=0
DXF ScaleY=0

--- DblcampBr2.p01 (plan) ---

Plan Title=Floodplain
Program Version=4.00
Geom File=g01
Flow File=f01
K Sum by GR=0
Std Step Tol=0.01
Critical Tol=0.01
Num of Std Step Trials=20
Max Error Tol=0.3
Flow Tol Ratio=0.001
Split Flow NTrial=30
Split Flow Tol=0.02
Split Flow Ratio=0.02
Log Output Level=0
Friction Slope Method=1
Unsteady Friction Slope Method=2
Unsteady Bridges Friction Slope Method=1
Global Log Level=0
CheckData=False
Run HTab=0
Run UNet=0
Run PostProcess=0
UNET Theta=0
UNET Theta Warmup=0
UNET ZTol=0
UNET ZSATol=0
UNET MxIter=0
UNET MaxInSteps=0
UNET DtIC=0
UNET DtMin=0
UNET MaxCRTS=0
UNET WFStab=0
UNET SFStab=0
UNET WFX=0
UNET SFX=0
UNET DSS MLevel=0
UNET DZMax Abort=0
UNET Convert EG Bridges=0
UNET Use Existing IB Tables=0
UNET Froude Limit=0
UNET Froude Power=0
Write IC File=0
Echo Input=False
Echo Output=False
Write Detailed=0

--- DblcampBr2.f01 (steady flow) ---

Flow Title=NFF Regression Equation
Program Version=4.00
Number of Profiles=1
Profile Names=P100yr
River Rch & RM=DblcampBr2,Main      ,2416
554.2213
River Rch & RM=DblcampBr2,Main      ,1486.1
573.5520
River Rch & RM=DblcampBr2,Main      ,218.8
628.0543
Boundary for River Rch & Prof#=DblcampBr2,Main      ,1
Up Type=0
Dn Type=3
Dn Slope=0.020813

--- DblcampBr2.g01 (geometry) ---

Geom Title=USGS 10m DEM
Program Version=4.00

River Reach=DblcampBr2     ,Main
Reach XY= 30
     1781590.197      222888.529     1781590.197      222844.868
     1781600.978      222793.661     1781612.836      222776.951
     1781666.738      222757.007     1781712.317      222724.971
     1781716.813      222690.286     1781716.813      222672.971
     1781702.314      222645.430     1781704.470      222592.067
     1781697.462      222558.648     1781671.050      222494.504
     1781676.198      222386.466     1781690.840      222324.164
     1781677.583      222276.981     1781684.486      222113.041
     1781667.184      222000.207     1781654.023      221973.473
     1781626.343      221849.215     1781599.361      221767.363
     1781589.119      221671.956     1781593.970      221569.003
     1781644.638      221433.170     1781690.455      221363.636
     1781734.960      221257.862     1781767.393      221213.189
     1781812.066      221114.665     1781873.261      221030.216
     1781870.201      220933.527     1781742.498      220654.267

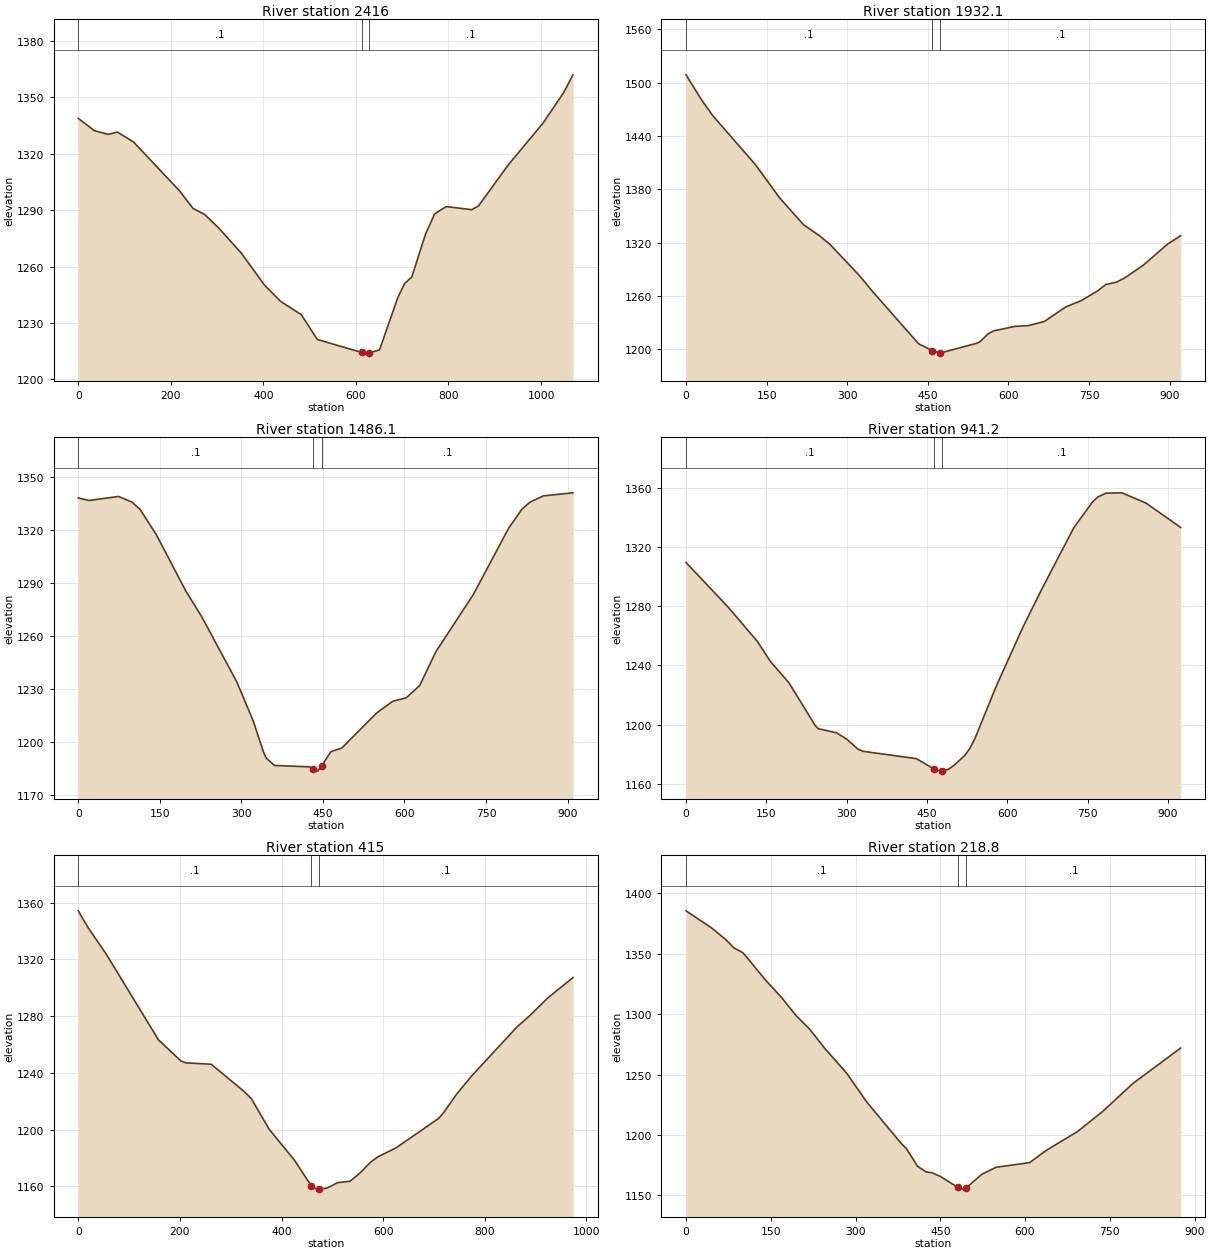
Type RM Length L Ch R = 1 ,2416,485.6,483.9,482.2
XS GIS Cut Line= 3
     1782208.949      222912.613     1781654.133      222872.158
     1781141.449      222878.529
#Sta/Elev= 30
       0 1338.79    34.8 1332.28    64.6 1330.30    84.4 1331.53   119.2 1326.33
   218.5 1300.32   248.3 1290.85   273.2 1287.68   303.0 1280.62   352.6 1267.05
   402.3 1250.16   437.1 1241.47   481.8 1234.44   516.6 1221.19   612.7 1214.26
   616.0 1213.92   627.7 1213.99   650.9 1215.59   690.7 1243.60   705.6 1251.07
   720.6 1254.33   750.4 1277.24   770.3 1288.07   795.2 1291.88   850.0 1290.24
   864.9 1292.22   929.6 1314.19  1004.3 1336.27  1049.1 1352.59  1069.0 1361.98
#Mann= 3 , 0 , 0
       0     0.1       0   612.7   0.045       0   627.7     0.1       0
Bank Sta=   612.7,   627.7
Exp/Cntr=0.3,0.1

Type RM Length L Ch R = 1 ,1932.1,450.2,446,441.8
XS GIS Cut Line= 3
     1782136.756      222435.558     1781555.885      222473.383
     1781220.283      222430.615
#Sta/Elev= 30
       0 1508.97    29.8 1479.99    49.8 1463.04   129.4 1407.75   174.1 1370.52
   218.9 1340.16   248.8 1327.71   268.7 1317.64   323.4 1282.58   348.3 1264.31
   432.8 1206.27   458.2 1198.68   472.6 1195.76   473.2 1195.84   542.3 1207.12
   547.3 1208.79   562.2 1217.52   572.2 1220.74   612.0 1225.88   636.8 1226.68
   666.7 1231.38   706.5 1247.70   736.3 1255.07   766.2 1265.97   781.1 1272.97
   801.0 1275.67   815.9 1280.22   850.8 1294.72   895.5 1318.18   920.4 1327.96
#Mann= 3 , 0 , 0
       0     0.1       0   458.2   0.045       0   473.2     0.1       0
Bank Sta=   458.2,   473.2
Exp/Cntr=0.3,0.1

Type RM Length L Ch R = 1 ,1486.1,529.5,544.8,560.1
XS GIS Cut Line= 3
     1782096.051      221920.009     1781654.818      222031.089
     1781213.645      222142.407
#Sta/Elev= 30
       0 1338.14    19.8 1336.70    74.2 1338.98    98.9 1335.75   113.8 1331.62
   143.4 1317.44   197.8 1285.45   227.5 1270.65   291.8 1233.86   321.5 1212.12
   341.2 1193.78   346.2 1190.69   361.0 1186.63   425.3 1185.86   432.6 1184.70
   440.2 1183.43   447.6 1186.41   464.9 1194.52   484.7 1196.48   549.0 1216.40
   578.6 1223.01   603.4 1224.97   628.1 1231.92   657.8 1251.02   727.0 1283.57
   791.3 1320.80   816.0 1331.69   830.9 1335.74   855.6 1339.31   910.0 1341.03
#Mann= 3 , 0 , 0
       0     0.1       0   432.6   0.045       0   447.6     0.1       0
Bank Sta=   432.6,   447.6
Exp/Cntr=0.3,0.1

Type RM Length L Ch R = 1 ,941.2,534,526.2,518.5
XS GIS Cut Line= 3
     1782066.930      221626.900     1781743.713      221557.359
     1781205.296      221308.187
#Sta/Elev= 30
       0 1309.74    79.0 1279.40   133.2 1256.31   157.9 1242.59   192.4 1228.19
   241.8 1199.05   246.7 1197.23   281.3 1194.35   301.0 1189.88   320.7 1183.42
   330.6 1181.86   430.3 1176.87   463.4 1169.80   475.2 1168.42   478.4 1168.66
   490.2 1169.67   500.1 1172.20   520.1 1178.81   530.0 1183.68   540.0 1190.82
   579.9 1226.36   629.8 1266.31   664.6 1291.74   724.5 1333.43   759.4 1350.79
   769.3 1354.14   784.3 1356.68   814.2 1356.92   859.1 1349.98   923.9 1333.47
#Mann= 3 , 0 , 0
       0     0.1       0   463.4   0.045       0   478.4     0.1       0
Bank Sta=   463.4,   478.4
Exp/Cntr=0.3,0.1

Type RM Length L Ch R = 1 ,415,204.2,196.2,188.2
XS GIS Cut Line= 3
     1782236.170      221292.291     1781992.224      221054.557
     1781363.894      220978.769
#Sta/Elev= 30
       0 1354.18    19.8 1342.09    54.3 1324.09   158.0 1263.20   202.4 1248.29
   212.3 1247.08   261.6 1246.09   325.8 1227.08   340.6 1221.88   375.5 1200.38
   425.3 1178.59   458.9 1160.27   465.2 1158.65   473.9 1158.13   475.2 1158.11
   490.1 1158.92   510.1 1162.65   535.0 1163.67   554.9 1169.65   574.8 1176.96
   589.8 1180.91   624.7 1187.02   709.4 1207.98   719.4 1212.19   744.3 1224.92
   774.2 1237.87   863.9 1272.58   888.8 1280.40   923.7 1292.74   973.5 1307.15
#Mann= 3 , 0 , 0
       0     0.1       0   458.9   0.045       0   473.9     0.1       0
Bank Sta=   458.9,   473.9
Exp/Cntr=0.3,0.1

Type RM Length L Ch R = 1 ,218.8,223.2,218.8,214.4
XS GIS Cut Line= 3
     1782318.757      220829.163     1781893.976      220837.832
     1781457.636      220950.529
#Sta/Elev= 30
       0 1385.48    45.0 1371.42    70.0 1361.86    85.0 1354.72   100.0 1351.05
   105.0 1348.56   140.0 1328.58   170.0 1313.31   194.9 1298.72   219.9 1287.03
   244.9 1272.05   284.9 1250.80   319.9 1227.26   379.9 1193.51   389.9 1188.81
   409.9 1174.04   424.9 1169.43   434.8 1168.81   449.6 1165.79   481.2 1156.62
   489.2 1155.17   496.2 1156.30   523.9 1167.56   548.7 1173.25   608.1 1177.07
   637.8 1187.28   692.3 1202.62   736.9 1219.21   791.3 1242.74   875.5 1271.96
#Mann= 3 , 0 , 0
       0     0.1       0   481.2   0.045       0   496.2     0.1       0
Bank Sta=   481.2,   496.2
Exp/Cntr=0.3,0.1